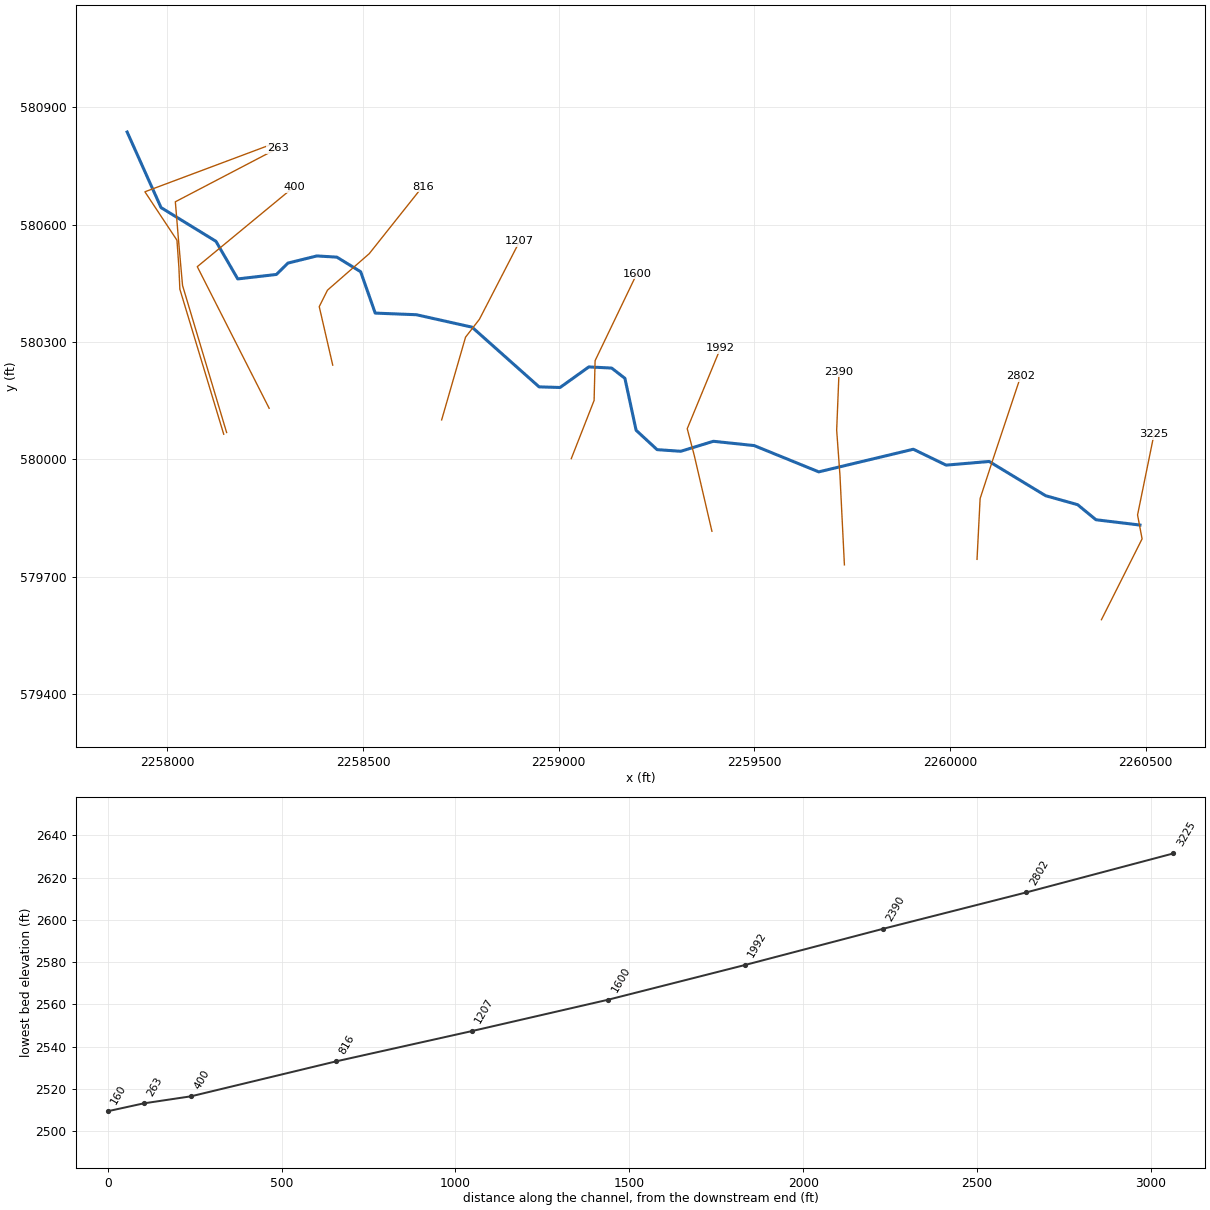
--- STWARTRNT1.prj (project) ---

Proj Title=STWARTRNT1
Current Plan=p01
Default Exp/Contr=0,0
English Units
Geom File=g01
Flow File=f01
Plan File=p01
BEGIN DESCRIPTION:
----------MODEL BY WOOD PLC 2022----------
AFH study
Randolph County, WV
HEC-RAS Version: RAS 6.2
Vertical Datum: NAVD88
Projection: NAD 1983 StatePlane West Virginia S FIPS 4702 (US Feet)
Terrain: 1-meter LIDAR (FEMA Region III 3DEP collected 2016-2018)
Land Use: 2019 NLCD
Hydrologic Method:
WV SIR2010-5033 regression equations
Additional Model Notes:
None
END DESCRIPTION:
DSS Export Rating Curves= 0
DSS Export Rating Curve Sorted= 0
DSS Export Volume Flow Curves= 0
DXF OffsetX= 0
DXF OffsetY= 0
DXF ScaleX= 0
DXF ScaleY= 0

--- STWARTRNT1.p01 (plan) ---

Plan Title=Floodplain
Program Version=6.20
Short Identifier=Floodplain
Geom File=g01
Flow File=f01
Subcritical Flow
K Sum by GR= 0
Std Step Tol= 0.01
Critical Tol= 0.01
Num of Std Step Trials= 20
Max Error Tol= 0.3
Flow Tol Ratio= 0.001
Split Flow NTrial= 30
Split Flow Tol= 0.02
Split Flow Ratio= 0.02
Log Output Level= 0
Friction Slope Method= 1
Unsteady Friction Slope Method= 2
Unsteady Bridges Friction Slope Method= 1
Parabolic Critical Depth
Global Vel Dist= 0 , 0 , 0
Global Log Level= 0
CheckData=True
Encroach Param=-1 ,0,0, 0
Mapping Interval=1HOUR
Computation Time Step Use Courant=        0
Computation Time Step Use Time Series=    0
Computation Time Step Count To Double=0
Computation Time Step Max Doubling=0
Computation Time Step Max Halving=0
Computation Time Step Residence Courant=0
Run HTab= 0
Run UNet= 0
Run Sediment= 0
Run PostProcess= 0
Run WQNet= 0
Run RASMapper=-1
UNET Theta= 0
UNET Theta Warmup= 0
UNET ZTol= 0
UNET ZSATol= 0
UNET MxIter= 0
UNET Max Iter WO Improvement= 0
UNET MaxInSteps= 0
UNET DtIC= 0
UNET DtMin= 0
UNET MaxCRTS= 0
UNET WFStab= 0
UNET SFStab= 0
UNET WFX= 1
UNET SFX= 1
UNET Gravity=32.174
UNET 1D Methodology=Finite Difference
UNET DSS MLevel= 1
UNET Pardiso=0
UNET DZMax Abort= 0
UNET Use Existing IB Tables= 0
UNET Froude Reduction=False
UNET Froude Limit= 0
UNET Froude Power= 0
UNET D1 Cores= 0
UNET WindReference=Eulerian
UNET WindDragFormulation=Hsu (1988)
UNET D2 Coriolis=0
UNET D2 Cores= 0
UNET D2 Theta= 1
UNET D2 Theta Warmup= 1
UNET D2 Z Tol= 0.01
UNET D2 Volume Tol= 0.01
UNET D2 Max Iterations= 20
UNET D2 Equation= 0
UNET D2 RampUpFraction=0.1
UNET D2 TimeSlices= 1
UNET D2 Turbulence Formulation=Non-Conservative (original)
UNET D2 Eddy Viscosity=0.3
UNET D2 Transverse Eddy Viscosity=0.1
UNET D2 Smagorinsky Mixing=0
UNET D2 BCVolumeCheck=0
UNET D2 Cores=0
UNET D2 SolverType=PARDISO (Direct)
UNET D2 Minimum Iterations= 2147483647
UNET D2 Maximum Iterations= 2147483647
UNET D2 Restart Number= 10
UNET D2 Relaxation Coeff=1.3
UNET D2 SOR Precondition Iterations= 10
UNET D2 ILUT Maximum Fill= 8
UNET D2 ILUT Tolerance=1E-08
UNET D1D2 MaxIter= 0
UNET D1D2 ZTol=0.01
UNET D1D2 QTol=0.1
UNET D1D2 MinQTol=1
Write IC File= 0
Write IC File at Fixed DateTime=0
Write IC File at Sim End=0
Echo Input=False
Echo Parameters=False
Echo Output=False
Write Detailed= 0
HDF Write Warmup=0
HDF Write Time Slices=0
HDF Flush=0
HDF Compression= 1
HDF Chunk Size= 1
HDF Spatial Parts= 1
HDF Use Max Rows=0
HDF Fixed Rows= 1
Calibration Method= 0
Calibration Iterations= 20
Calibration Max Change=0.05
Calibration Tolerance=0.2
Calibration Maximum=1.5
Calibration Minimum=0.5
Calibration Optimization Method= 1
WQ AD Non Conservative
WQ ULTIMATE=-1
WQ Max Comp Step=1HOUR
WQ Output Interval=15MIN
WQ Output Selected Increments= 0
WQ Output face flow=0
WQ Output face velocity=0
WQ Output face area=0
WQ Output face dispersion=0
WQ Output cell volume=0
WQ Output cell surface area=0
WQ Output cell continuity=0
WQ Output cumulative cell continuity=0
WQ Output face conc=0
WQ Output face dconc_dx=0
WQ Output face courant=0
WQ Output face peclet=0
WQ Output face adv mass=0
WQ Output face disp mass=0
WQ Output cell mass=0
WQ Output cell source sink temp=0
WQ Output nsm pathways=0
WQ Output nsm derived pathways=0
WQ Create Restart=0
WQ Fixed Restart=0
WQ System Summary=0
WQ Write To DSS=0
Sorting and Armoring Iterations= 10
XS Update Threshold= 0.02
Bed Roughness Predictor= 0
Hydraulics Update Threshold= 0.02
Energy Slope Method= 1
Volume Change Method= 1
Sediment Retention Method= 0
Sediment TS Multiplier= 1
Warm Up Method= 0
XS Weighting Method= 0
Number of US Weighted Cross Sections= 1
Number of DS Weighted Cross Sections= 1
Upstream XS Weight=0
Main XS Weight=1
Downstream XS Weight=0
Number of DS XS's Weighted with US Boundary= 1
Upstream Boundary Weight= 1
Weight of XSs Associated with US Boundary= 0
Number of US XS's Weighted with DS Boundary= 1
Downstream Boundary Weight= 0.5
Weight of XSs Associated with DS Boundary= 0.5
Percentile Method= 0
Sediment Output Level= 3
Mass or Volume Output= 0
Output Increment Type= 1
Profile and TS Output Increment= 1
Transport Output Increment 1
XS Output Flag= 0
XS Output Increment= 10
Read HDF5 Sediment Hotstart= 0
Sediment Hotstart Type= 0
Write Gradation File= 0
Read Gradation Hotstart= 0
Write HDF5 File= 1
Write Binary Output= 1
Write DSS Sediment File= 0
DSS Sediment Output Type= 1
SV Curve= 0
Specific Gage Flag= 0
Subcell Erosion Methods= 0
Subcell Deposition Methods= 0
Advection Scheme= 1
Matrix Solver= 0
Implicit Weighting Factor= 1
Maximum Outer Loop Convergence Iterations= 5
Convergence Maximum Absolute= 0.001
Convergence RMSE= 0.0001
Grain Fractions Max Abs Error= 0.001
Max Subgrid Regions= 1
Max Subgrid Length Scale= 3.402823E+38
Initial Layer Thickness= 3.402823E+38
Min Layer Thickness= 3.402823E+38
Max Layer Thickness= 3.402823E+38
Number of Layers= 5

--- STWARTRNT1.f01 (steady flow) ---

Flow Title=Flow
Program Version=6.20
Number of Profiles= 1
Profile Names=P100yr
River Rch & RM=STWARTRNT1,Main,3225
     425
Boundary for River Rch & Prof#=STWARTRNT1,Main            , 1
Up Type= 0
Dn Type= 3
Dn Slope=0.02965
DSS Import GetInterval= 0
DSS Import GetPeak= 0
DSS Import FillOption= 0

--- STWARTRNT1.g01 (geometry) ---

Geom Title=Geometry
Program Version=6.20

River Reach=STWARTRNT1      ,Main
Reach XY= 30
2260485.23600003579832.1930000042260372.73600002579845.735000014
     2260325.861579884.2759999932260244.08999999579907.193000004
2260099.82000002579994.6930000042259989.92400001579985.318000004
2259906.06999999580025.9430000192259664.40300003 579968.13000001
2259499.29899998580035.3180000192259395.13200003580046.256000027
     2259311.799580020.7349999992259251.38200003580024.900999993
2259197.73600003580074.3809999972259169.09000003580207.165254503
2259135.22675152580233.3778937762259076.90300001580236.312757522
     2259003.465580183.7560000122258949.81999999580185.318000019
2258778.46500003580337.9220000062258636.27800003580369.693000004
2258531.06900001580373.859999999     2258493.873580479.545000017
     2258433.109580516.8719999942258381.89400002580519.909999996
2258308.11000001580501.681000009     2258278.596580472.601000011
2258179.75300005580461.2020000072258124.07100001      580557.338
2257983.80500005580643.446999997     2257897.159      580836.617

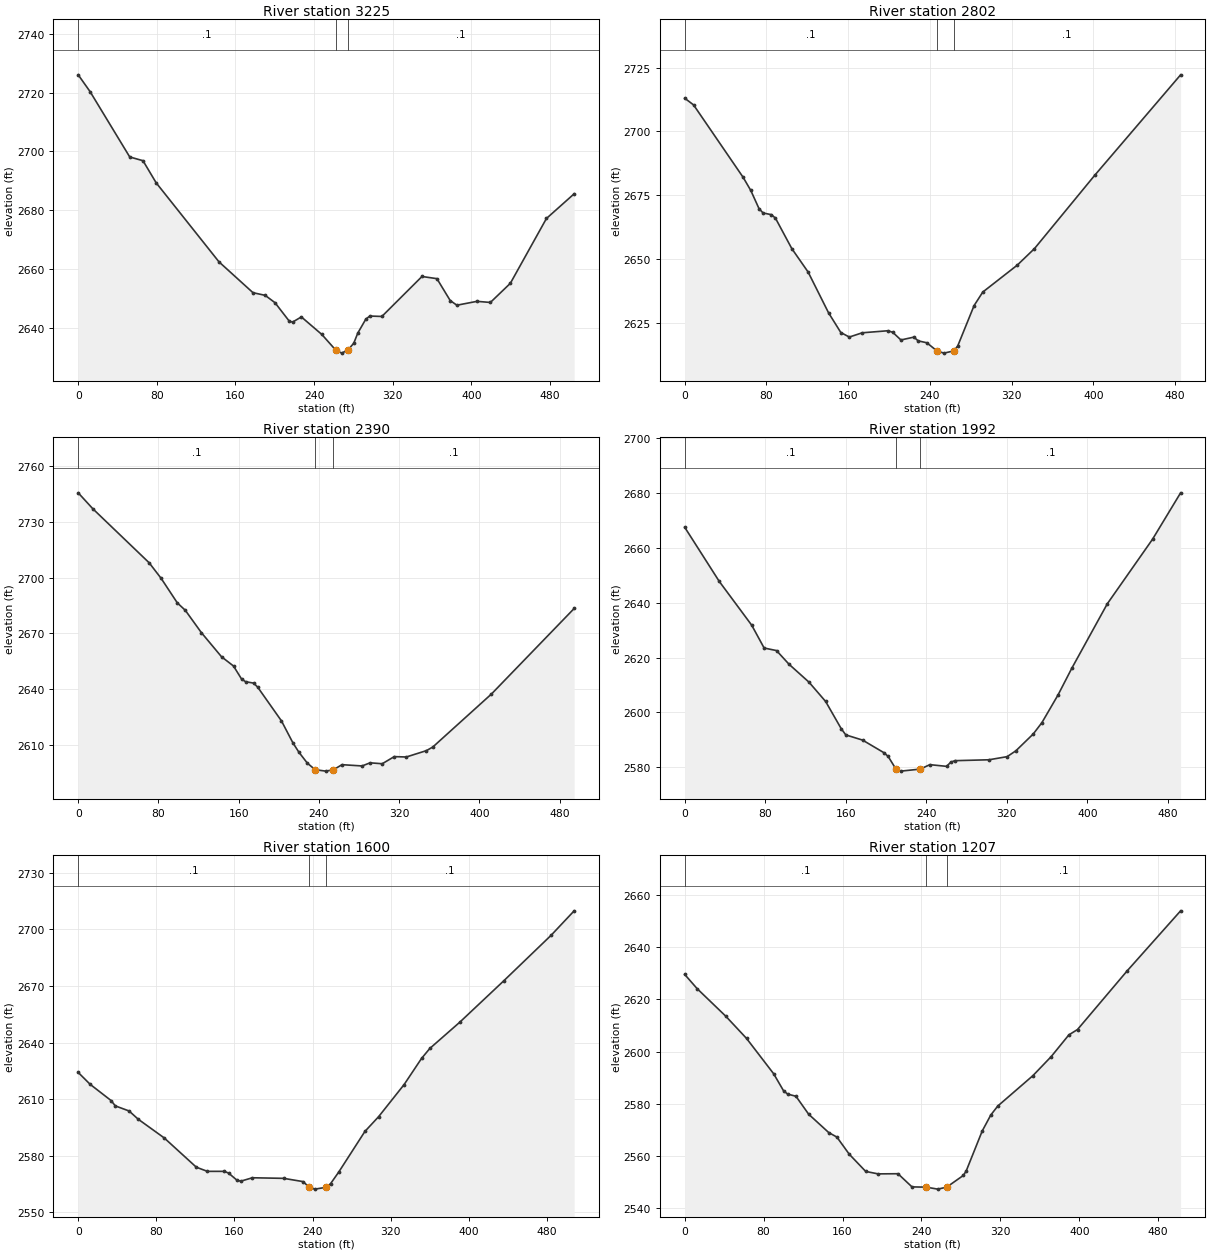
Type RM Length L Ch R = 1 ,3225    ,424.8,422.7,418.7
XS GIS Cut Line= 4
2260386.73117795579590.3442481712260490.59905659  579796.8771413
2260479.03590369579858.0938331232260521.21621689580064.863720778
#Sta/Elev= 30
       0 2726.03    12.1 2720.31    52.4 2698.13    65.9 2696.85    79.3 2689.34
   143.2 2662.49   177.8 2652.01   190.2 2651.11   200.2 2648.61   214.7 2642.34
   218.1 2642.03     227 2643.78   247.8 2637.83  261.78 2632.58   268.1 2631.48
  274.41 2632.58   280.3 2634.84   284.4 2638.29   292.5 2642.99   296.6 2644.08
   308.9 2643.94   349.7 2657.52   364.9 2656.78   378.4 2649.35   385.2 2647.76
   405.6 2649.07   419.3  2648.7   439.6  2655.2   476.3 2677.22   504.5 2685.61
#Mann= 3 ,-1,0
       0      .1       0  261.78    .045       0  274.41      .1       0
Bank Sta=261.78,274.41
XS Rating Curve= 0 ,0
Exp/Cntr(USF)=0,0
Exp/Cntr=0.3,0.1

Type RM Length L Ch R = 1 ,2802    ,409.1,412.1,415.2
XS GIS Cut Line= 4
2260068.82803897 579744.530173982260076.72044424579899.896645162
 2260110.3098499580002.5309402472260180.60698453580212.887608668
#Sta/Elev= 30
       0 2713.02     8.7 2710.38    57.2 2681.98    64.7 2676.82    72.7 2669.74
    76.7    2668    84.8 2667.34    88.8 2665.99   104.8 2654.04   120.8 2644.83
   140.8 2628.83   152.8 2621.11   161.1 2619.34   173.8 2621.01     199 2621.81
   203.7 2621.17   211.6 2618.19   224.3 2619.31   228.5 2617.84   236.9  2617.1
  246.922613.894   253.7 2613.03  263.232613.894   267.1 2615.75   283.2 2631.68
   291.7 2636.98   325.4 2647.52   342.3 2654.03   401.3  2682.8   485.3 2722.18
#Mann= 3 ,-1,0
       0      .1       0  246.92    .045       0  263.23      .1       0
Bank Sta=246.92,263.23
XS Rating Curve= 0 ,0
Exp/Cntr(USF)=0,0
Exp/Cntr=0.3,0.1

Type RM Length L Ch R = 1 ,2390    ,396.3,398.7,402.3
XS GIS Cut Line= 4
2259729.95104275579730.492061778 2259718.5804244579959.591746692
2259710.18307298580074.635461092 2259716.2592647580224.331479207
#Sta/Elev= 30
       0  2745.6    14.7 2736.95    70.8 2707.91    82.8 2699.48    98.8 2686.38
   106.8 2682.36   122.8 2670.36   142.9 2657.36   154.9 2652.35   162.9 2645.37
   166.9 2643.93   174.9 2643.16   178.9 2641.05   202.7 2622.82   214.1 2611.02
   220.1 2605.95   228.5 2600.09  236.312596.541     247 2595.78  254.562596.541
   263.1 2599.25   283.1 2598.57   291.1 2600.25   303.2 2599.76   315.2 2603.59
   327.2 2603.39   347.3 2606.82   353.7 2608.79   412.1 2637.28   494.6 2683.33
#Mann= 3 ,-1,0
       0      .1       0  236.31    .045       0  254.56      .1       0
Bank Sta=236.31,254.56
XS Rating Curve= 0 ,0
Exp/Cntr(USF)=0,0
Exp/Cntr=0.3,0.1

Type RM Length L Ch R = 1 ,1992    ,392.7,391.6,379.1
XS GIS Cut Line= 4
2259391.42090713579816.3146293572259346.07457387580011.079623266
2259328.32173324580078.4179842712259413.35992903580284.411744746
#Sta/Elev= 30
       0 2667.51    34.3 2647.77    66.6 2631.76    78.9 2623.46    91.2 2622.53
   103.6 2617.55   123.4 2611.03     140 2603.96   155.4 2594.08     160 2591.78
   176.7 2589.88     198 2585.26   202.1 2583.91   209.8 2579.31   214.6 2578.57
  233.94 2579.31   243.5 2580.93   260.1 2580.31   264.2 2581.81   268.3 2582.38
   302.2 2582.71   320.2 2583.85   328.9 2585.98   346.2 2592.14   354.8 2596.28
   370.8 2606.37   384.5 2616.13   419.7 2639.59   464.6 2663.12   492.5 2680.05
#Mann= 3 ,-1,0
       0      .1       0   209.8    .045       0  233.94      .1       0
Bank Sta=209.8,233.94
XS Rating Curve= 0 ,0
Exp/Cntr(USF)=0,0
Exp/Cntr=0.3,0.1

Type RM Length L Ch R = 1 ,1600    ,396.9,392.9,384.7
XS GIS Cut Line= 4
2259032.00475333580001.8214007972259090.36659294580150.616645217
 2259092.9128565580252.3104369442259199.53405327580474.383754136
#Sta/Elev= 30
       0 2624.13    12.2 2617.83    33.6 2609.24      38 2606.38    52.1 2603.68
    61.4 2599.33    88.1 2589.37     121 2573.83   132.3 2571.64   149.7 2571.64
     154 2570.72   162.4 2567.03   166.4 2566.42   178.4 2568.24   210.4 2567.93
   230.4 2566.19  236.622563.137   242.4 2562.21  253.442563.138   258.4 2565.07
     267 2571.42   293.6 2592.82   307.7 2600.69   333.8 2617.73   351.6 2631.56
   360.1 2636.87   390.6 2650.71   435.6 2672.64   484.4 2696.96   507.9 2709.89
#Mann= 3 ,-1,0
       0      .1       0  236.62    .045       0  253.44      .1       0
Bank Sta=236.62,253.44
XS Rating Curve= 0 ,0
Exp/Cntr(USF)=0,0
Exp/Cntr=0.3,0.1

Type RM Length L Ch R = 1 ,1207    ,391.8,390.7,392
XS GIS Cut Line= 4
2258700.81652975580100.9054546062258761.85782505580312.326913187
2258797.31330881580358.0458264522258900.35138712580557.877460805
#Sta/Elev= 30
       0 2629.56    12.6 2624.11    41.7 2613.53    62.7 2605.04    90.2  2591.5
   100.2 2584.99   104.4 2583.71   112.8 2582.88   125.7 2575.99     146 2568.98
   154.3 2567.24   166.8 2560.69   183.5 2554.09     196 2553.15   216.2 2553.21
   230.4 2548.17  244.912548.063   256.5 2547.31  265.572548.063   282.4 2552.54
   285.3 2554.21   301.6 2569.58   310.3 2575.71   317.4 2579.15   352.9 2590.75
   371.5 2598.07   389.4 2606.38   398.2 2608.45   448.6 2630.95   502.7 2653.91
#Mann= 3 ,-1,0
       0      .1       0  244.91    .045       0  265.57      .1       0
Bank Sta=244.91,265.57
XS Rating Curve= 0 ,0
Exp/Cntr(USF)=0,0
Exp/Cntr=0.3,0.1

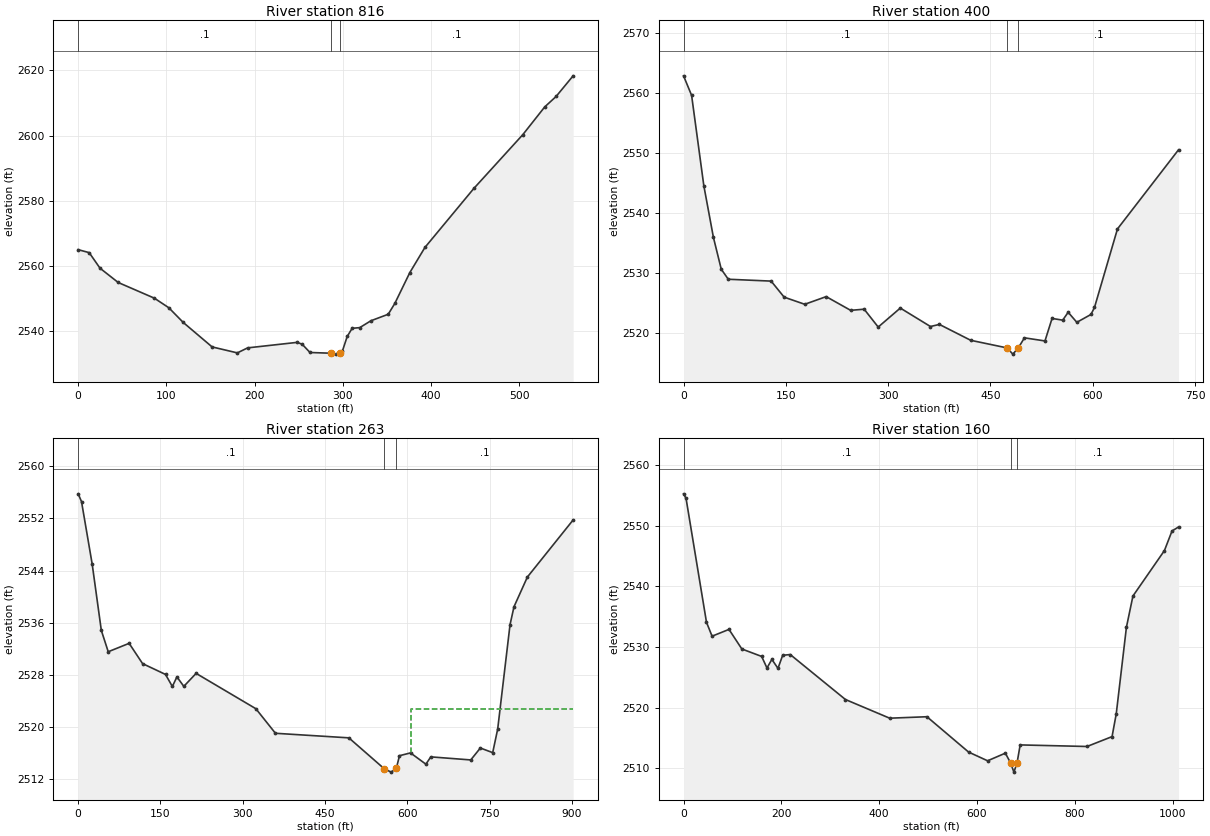
Type RM Length L Ch R = 1 ,816     ,416.2,416.4,411.4
XS GIS Cut Line= 5
2258422.45165996580240.9776691942258388.02614069580390.389617048
2258409.05508033580432.4643820652258515.83621562580525.768286688
 2258652.2104556580697.314444293
#Sta/Elev= 30
       0 2565.01    12.5  2564.1    24.8 2559.32    45.4 2554.94    86.4 2550.13
   102.8 2547.19   119.2 2542.67   151.9 2535.17   180.5 2533.34   192.2 2534.88
   248.4 2536.57   254.1 2535.98   262.9 2533.46286.5675 2533.24   292.6 2532.96
297.24752533.245   299.5 2533.77   305.1 2538.38   310.7 2540.88   319.3 2541.09
     332  2543.2   351.6 2545.19   359.1 2548.51   376.1 2557.97   393.2 2565.68
   448.7 2583.79   504.3 2600.32   529.1 2608.81     542 2612.02   561.3 2618.35
#Mann= 3 ,-1,0
       0      .1       0286.5675    .045       0297.2475      .1       0
Bank Sta=286.5675,297.2475
XS Rating Curve= 0 ,0
Exp/Cntr(USF)=0,0
Exp/Cntr=0.3,0.1

Type RM Length L Ch R = 1 ,400     ,130.1,136.9,148.8
XS GIS Cut Line= 3
2258260.01353452580130.6819247982258076.39748491580492.484531401
 2258323.1688601 580696.17659108
#Sta/Elev= 30
       0  2562.9    11.8 2559.64    29.7 2544.57    43.8 2535.92    55.3 2530.61
    65.6 2528.94   128.4 2528.63   147.5 2525.95   177.7 2524.76   209.1 2526.04
     245 2523.75   264.8 2523.94   285.4 2520.96   317.8 2524.13     362 2521.05
   375.1  2521.4     421 2518.75  474.382517.476   482.8 2516.44  490.742517.474
   499.8 2519.16   529.9 2518.64   540.3  2522.4   555.9 2522.11   563.9 2523.43
   576.6 2521.75   597.3 2523.06   602.5 2524.23   636.2 2537.34   725.7 2550.55
#Mann= 3 ,-1,0
       0      .1       0  474.38    .045       0  490.74      .1       0
Bank Sta=474.38,490.74
XS Rating Curve= 0 ,0
Exp/Cntr(USF)=0,0
Exp/Cntr=0.3,0.1

Type RM Length L Ch R = 1 ,263     ,110.5,102.8,86.6
XS GIS Cut Line= 5
2258151.34025056580068.7182374032258038.72282356580444.481272282
2258028.34263841580561.2551533292258020.35712988580658.330965902
2258282.09116347580795.112198066
#Sta/Elev= 30
       0 2555.77     6.1 2554.58    25.5 2545.02    42.2 2534.82    54.8 2531.54
    92.9 2532.83   117.4 2529.72   159.2 2528.06   171.7 2526.21     180 2527.68
   192.6 2526.23     215 2528.22   323.9  2522.8   359.6 2519.03   493.4 2518.33
   557.6 2513.61   570.5 2513.07  579.89 2513.64   585.7 2515.59   605.8 2516.02
   633.8 2514.29   642.8 2515.41   715.6 2514.94   733.1 2516.77   755.6 2516.06
   764.7 2519.68   787.2 2535.69   794.4 2538.44   818.8    2543   902.2 2551.76
#Mann= 3 ,0,0
       0      .1       0   557.6    .045       0  579.89      .1       0
#XS Ineff= 2 , 0
                          607.19         2522.79
Permanent Ineff=
       F       F
Bank Sta=557.6,579.89
XS Rating Curve= 0 ,0
Exp/Cntr(USF)=0,0
Exp/Cntr=0.3,0.1

Type RM Length L Ch R = 1 ,160     ,,,
XS GIS Cut Line= 6
 2258143.9418638580064.289396026 2258031.8533842580435.043597799
2258029.38990113580491.0878376022258024.46293499580560.065363513
2257942.55212297580683.8553876932258271.42711258580807.029541106
#Sta/Elev= 30
       0 2555.28     5.1 2554.53    46.9 2534.09    58.3 2531.79    92.9 2532.91
   119.2 2529.68   159.7 2528.45   170.6 2526.54   180.6 2527.96   193.1 2526.48
   202.7 2528.64   218.2 2528.76   331.1 2521.34   421.5 2518.26   497.7  2518.5
   582.9 2512.67   621.8 2511.23   658.1 2512.49  668.61  2510.9   675.6 2509.36
     682 2510.88   688.4 2513.85   825.1 2513.59   876.3 2515.22   884.9    2519
   905.7 2533.28     919 2538.42   983.4 2545.92   998.9 2549.15  1012.2 2549.81
#Mann= 3 ,0,0
       0      .1       0  668.61    .045       0     682      .1       0
Bank Sta=668.61,682
XS Rating Curve= 0 ,0
Exp/Cntr(USF)=0,0
Exp/Cntr=0.3,0.1
LCMann Table=0

Chan Stop Cuts=-1
Use User Specified Reach Order=0
Composite Channel Slope=5